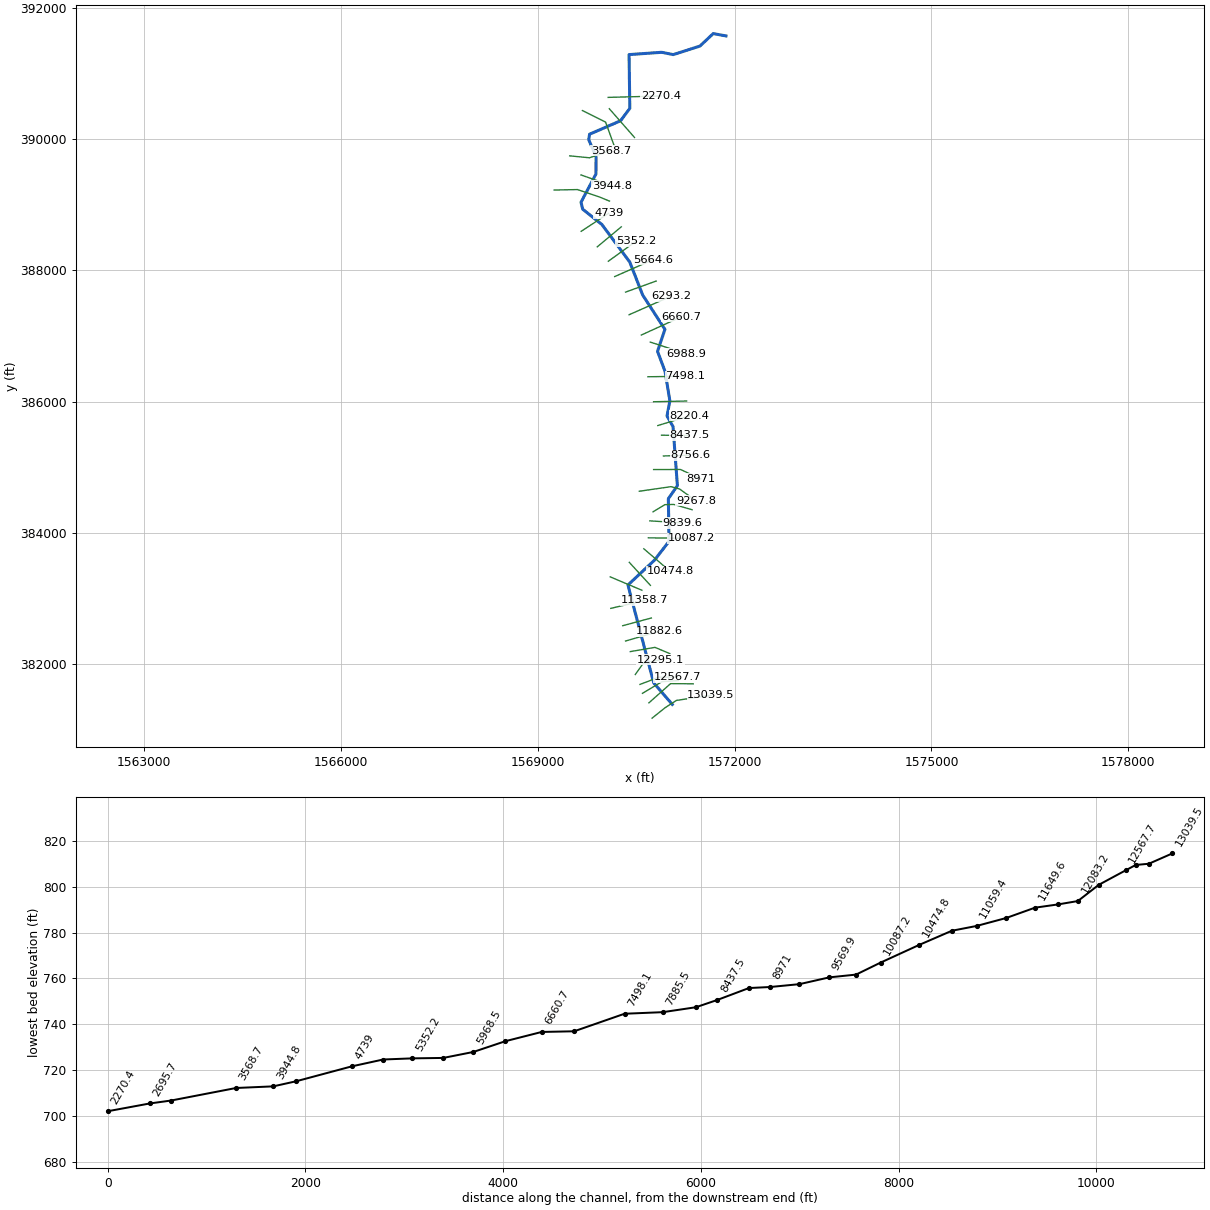
--- RFRICHCR.prj (project) ---

Proj Title=RFRICHCR
Current Plan=p01
Default Exp/Contr=0,0
English Units
Geom File=g01
Flow File=f01
Plan File=p01
BEGIN DESCRIPTION:
END DESCRIPTION:
DSS File=dss
DSS Export Rating Curves= 0
DSS Export Rating Curve Sorted= 0
DSS Export Volume Flow Curves= 0
DXF OffsetX= 0
DXF OffsetY= 0
DXF ScaleX= 0
DXF ScaleY= 0

--- RFRICHCR.p01 (plan) ---

Plan Title=Floodplain
Program Version=4.00
Short Identifier=Floodplain
Geom File=g01
Flow File=f01
Subcritical Flow
K Sum by GR= 0
Std Step Tol= 0.01
Critical Tol= 0.01
Num of Std Step Trials= 20
Max Error Tol= 0.3
Flow Tol Ratio= 0.001
Split Flow NTrial= 30
Split Flow Tol= 0.02
Split Flow Ratio= 0.02
Log Output Level= 0
Friction Slope Method= 1
Unsteady Friction Slope Method= 2
Unsteady Bridges Friction Slope Method= 1
Parabolic Critical Depth
Global Vel Dist= 0 , 0 , 0
Global Log Level= 0
CheckData=True
Encroach Param=-1 ,0,0, 0
Run HTab= 0
Run UNet= 0
Run PostProcess= 0
Run WQNet= 0
UNET Theta= 0
UNET Theta Warmup= 0
UNET ZTol= 0
UNET ZSATol= 0
UNET MxIter= 0
UNET MaxInSteps= 0
UNET DtIC= 0
UNET DtMin= 0
UNET MaxCRTS= 0
UNET WFStab= 0
UNET SFStab= 0
UNET WFX= 1
UNET SFX= 1
UNET DSS MLevel= 1
UNET DZMax Abort= 0
UNET Convert EG Bridges= 0
UNET Use Existing IB Tables= 0
UNET Froude Reduction=False
UNET Froude Limit= 0
UNET Froude Power= 0
UNET Time Slicing=0,0, 5
DSS File=dss
Write IC File= 0
Echo Input=False
Echo Output=False
Write Detailed= 0
Detailed Automatic Start=False, 0
WQ ULTIMATE=-1
WQ Max Comp Step=1HOUR
WQ Output Interval=15MIN
WQ Output Selected Increments= 0
WQ Output face flow=0
WQ Output face velocity=0
WQ Output face area=0
WQ Output face dispersion=0
WQ Output cell volume=0
WQ Output cell surface area=0
WQ Output cell continuity=0
WQ Output face conc=0
WQ Output face dconc_dx=0
WQ Output face courant=0
WQ Output face peclet=0
WQ Output face adv mass=0
WQ Output face disp mass=0
WQ Output cell mass=0
WQ Output cell source sink temp=0
WQ Output cell source sink nsm=0
WQ Output MaxMinRange=-1
WQ Daily Max Min Mean=-1
WQ Daily Range=0
WQ Daily Time=0
WQ Create Restart=0
WQ Fixed Restart=0
WQ System Summary=False
Sorting and Armoring Iterations= 10
XS Update Threshold= 0.02
Hydraulics Update Threshold= 0.02
Energy Slope Method= 1
Volume Change Method= 0
XS Weighting Method= 0
Number of US Weighted Cross Sections= 1
Number of DS Weighted Cross Sections= 1
Upstream XS Weight=0.25
Main XS Weight=0.5
Downstream XS Weight=0.25
Number of DS XS's Weighted with US Boundary= 1
Upstream Boundary Weight= 1
Weight of XSs Associated with US Boundary= 0
Number of US XS's Weighted with DS Boundary= 1
Downstream Boundary Weight= 0.5
Weight of XSs Associated with DS Boundary= 0.5
Sediment Output Level= 4
Mass or Volume Output= 0
Output Increment Type= 1
Profile and TS Output Increment= 10
XS Output Flag= 0
XS Output Increment= 10
Disregard all LS=0
Disregard all Conn=0
Disregard all Breaches=0
Disregard all Pumps=0

--- RFRICHCR.f01 (steady flow) ---

Flow Title=NFF Regression Equation
Program Version=4.00
Number of Profiles=1
Profile Names=P100yr
River Rch & RM=RFRICHCR,Main      ,13039.5
     355
River Rch & RM=RFRICHCR,Main      ,12567.7
360.3189
River Rch & RM=RFRICHCR,Main      ,12295.1
429.8147
River Rch & RM=RFRICHCR,Main      ,11358.7
442.2665
River Rch & RM=RFRICHCR,Main      ,11059.4
514.7260
River Rch & RM=RFRICHCR,Main      ,10474.8
521.7812
River Rch & RM=RFRICHCR,Main      ,9569.9
577.1443
River Rch & RM=RFRICHCR,Main      ,9267.8
685.1206
River Rch & RM=RFRICHCR,Main      ,8971
731.7667
River Rch & RM=RFRICHCR,Main      ,5664.6
808.0857
River Rch & RM=RFRICHCR,Main      ,4178
897.8086
River Rch & RM=RFRICHCR,Main      ,293.1
967.4886
Boundary for River Rch & Prof#=RFRICHCR,Main      ,1
Up Type=0
Dn Type=3
Dn Slope=0.008483

--- RFRICHCR.g01 (geometry) ---

Geom Title=Geometry
Program Version=4.00

River Reach=RFRICHCR        ,Main
Reach XY= 30
     1571049.616      381383.397     1570765.715      381712.135
      1570372.91      383204.351     1570778.281      383584.144
     1570999.263      383869.863     1570988.879      384520.152
     1571126.815      384718.941     1571059.876      385619.579
     1570968.443      385780.643     1571011.909      386011.986
      1570937.73      386463.642     1570823.656      386767.967
     1570936.514      387101.329     1570596.533      387626.775
     1570401.245      388127.006     1569975.013      388701.209
     1569683.172      388933.776       1569657.1      389039.966
     1569885.231      389470.197     1569886.537      389732.083
      1569774.73      389995.691     1569788.576      390077.901
     1570259.259      390281.403     1570401.542      390471.649
     1570389.731      391290.999     1570886.662      391325.896
     1571063.661      391290.902     1571470.154      391420.747
     1571673.532      391611.373     1571867.464      391575.417

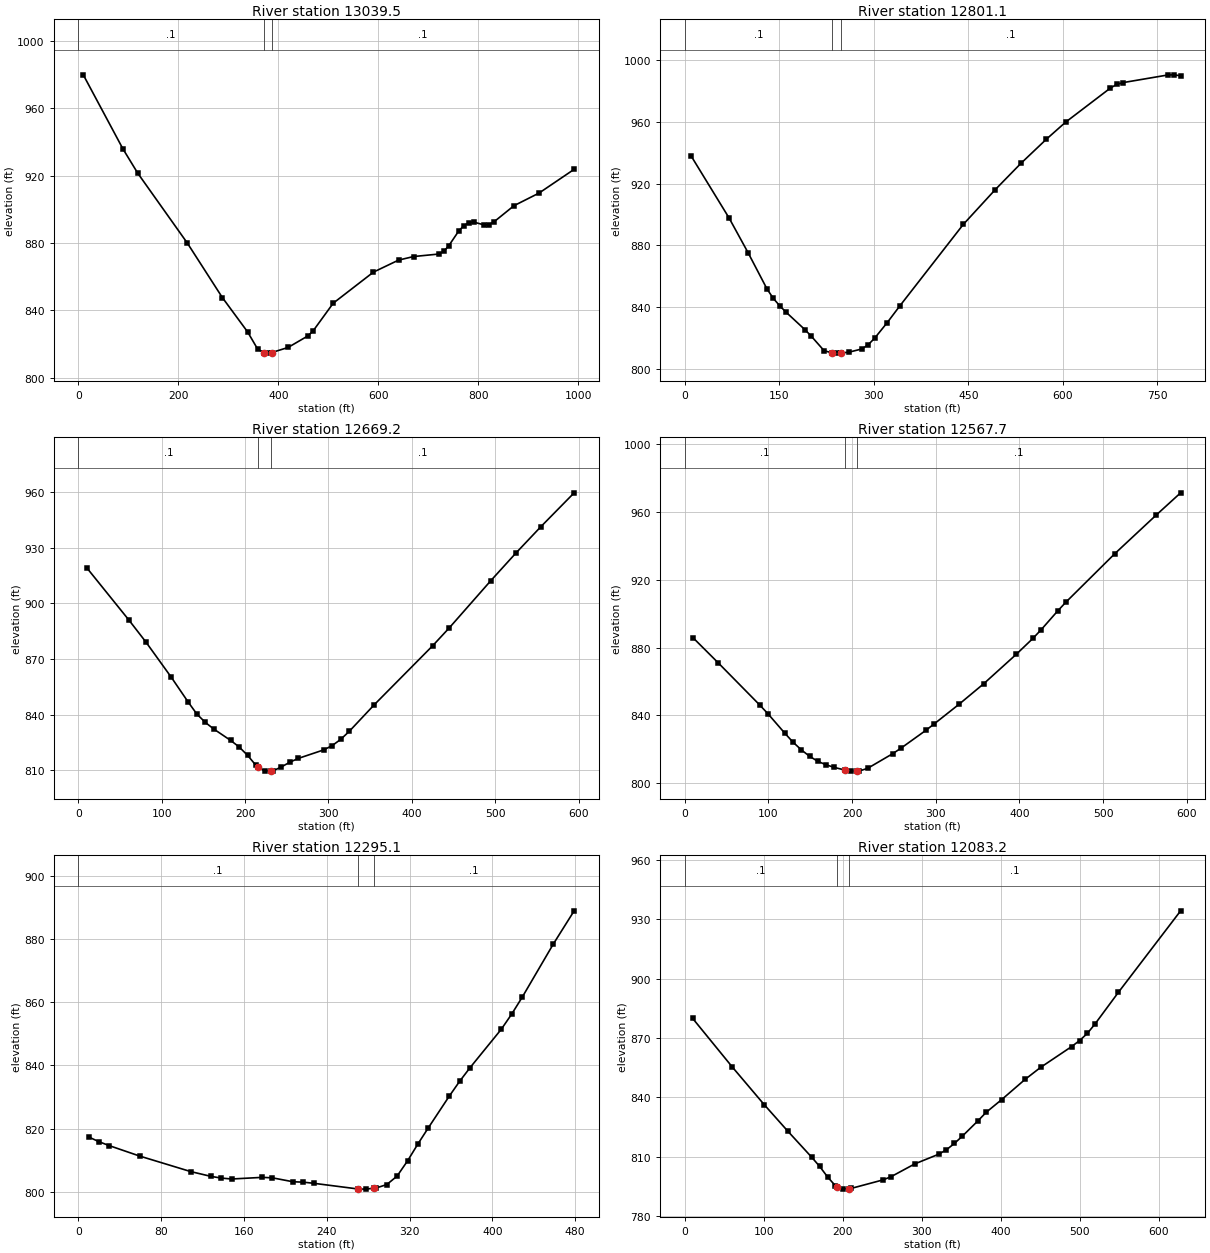
Type RM Length L Ch R = 1 ,13039.5 ,234.9,238.3,241.8
XS GIS Cut Line= 4
     1570741.265      381174.841     1570942.539       381335.86
     1571112.184      381445.123     1571638.371      381522.757
#Sta/Elev= 30
     9.9  979.95    89.2   935.9     119  921.39   218.1  879.86     288  847.52
   338.5  827.11   358.6  816.87   371.3  814.73   378.8   814.5   386.3  814.81
   419.2  817.85   459.5  824.82   469.6  827.78   509.7   844.2     590  862.65
   640.2  869.79   670.3  871.92   720.5   873.4   730.5  874.94   740.5  878.25
   760.6   887.1   770.6  890.26   780.7  892.01   790.7  892.41   810.8  890.77
   820.8  890.88   830.9   892.5     871  902.13   921.2  909.66   991.4  923.77
#Mann= 3 , 0 , 0
       0      .1       0   371.3    .045       0   386.3      .1       0
Bank Sta=371.3,386.3
XS Rating Curve= 0 ,0
Exp/Cntr=0.3,0.1

Type RM Length L Ch R = 1 ,12801.1 ,136.2,132,127.8
XS GIS Cut Line= 3
     1570692.384      381407.744     1571023.049      381701.028
     1571368.089      381698.153
#Sta/Elev= 30
      10  937.92    70.3  897.65   100.5  875.09   130.6  851.52   140.6  845.44
   150.7  840.67   160.7  836.56   190.9  825.12   200.9  820.91     221   811.6
   233.6  810.12   241.1  809.98   248.6  810.09   261.2  810.67   281.3  812.71
   291.3  815.51   301.4   819.7   321.4  829.83   341.5  840.72     442  893.47
   492.7  916.03   533.3  933.02   573.9  948.77   604.4  959.81   675.4  981.92
   685.6  984.35   695.7   985.5   766.7  990.44   776.9  990.54     787   989.9
#Mann= 3 , 0 , 0
       0      .1       0   233.6    .045       0   248.6      .1       0
Bank Sta=233.6,248.6
XS Rating Curve= 0 ,0
Exp/Cntr=0.3,0.1

Type RM Length L Ch R = 1 ,12669.2 ,105.4,101.4,97.5
XS GIS Cut Line= 3
      1570594.62      381553.203      1570890.82      381730.215
     1571139.817      381747.916
#Sta/Elev= 30
    10.1  919.24    60.9  890.88    81.2  879.07   111.6  860.07   131.9  846.66
   142.1  840.32   152.2  835.81   162.4  832.21   182.7  826.04   192.8  822.55
     203     818   213.1  812.55   215.8  811.74   223.3  809.47   230.8  809.57
   233.4  809.61   243.6  811.74   253.7   814.3   263.9  816.35   294.3  820.93
   304.5  823.26   314.6  826.58   324.8  830.88     355  845.33   424.9  877.11
   444.9  886.79   494.8  912.32   524.8  927.17   554.7  941.39   594.7   959.7
#Mann= 3 , 0 , 0
       0      .1       0   215.8    .045       0   230.8      .1       0
Bank Sta=215.8,230.8
XS Rating Curve= 0 ,0
Exp/Cntr=0.3,0.1

Type RM Length L Ch R = 1 ,12567.7 ,276,272.6,269.2
XS GIS Cut Line= 3
     1570556.858      381688.913     1570844.777       381798.79
     1571129.436       381798.79
#Sta/Elev= 30
     9.9   885.8    39.8  871.09    89.5  846.18    99.4  840.98   119.3  829.65
   129.2  824.31   139.2  819.73   149.1  815.91   159.1   812.9     169  810.84
   178.9   809.3   191.3  807.78   198.8  807.13   206.3   807.2   208.8  807.22
   218.7  808.81   248.5   817.4   258.5  820.68   288.3  831.22   298.2     835
   327.8  846.55   357.3  858.65   396.5  876.14   416.1  885.39     426  890.53
   445.6  901.51   455.4   906.7   514.3  935.51   563.4  958.11   592.8  971.32
#Mann= 3 , 0 , 0
       0      .1       0   191.3    .045       0   206.3      .1       0
Bank Sta=191.3,206.3
XS Rating Curve= 0 ,0
Exp/Cntr=0.3,0.1

Type RM Length L Ch R = 1 ,12295.1 ,212.9,211.9,211
XS GIS Cut Line= 3
     1570484.873      381839.963     1570605.241      382008.714
     1570870.759      382066.538
#Sta/Elev= 30
     9.9  817.35    19.7  815.87    29.6  814.62    59.2  811.29   108.6  806.36
   128.3  804.83   138.2   804.3   148.1  804.01   177.7  804.53   187.5  804.38
   207.3  803.14   217.3  803.01   227.4  802.65   270.2  800.85   277.7   800.8
   285.2  801.08   287.8  801.18   297.9  802.23   307.9  804.92     318  809.73
   328.1  815.15   338.1  820.23   358.2  830.21   368.3  834.96   378.4   839.3
   408.6  851.49   418.6  856.27   428.7  861.59   458.9  878.53     479  889.04
#Mann= 3 , 0 , 0
       0      .1       0   270.2    .045       0   285.2      .1       0
Bank Sta=270.2,285.2
XS Rating Curve= 0 ,0
Exp/Cntr=0.3,0.1

Type RM Length L Ch R = 1 ,12083.2 ,198.1,200.6,203.1
XS GIS Cut Line= 3
     1570408.555      382188.977     1570784.512      382253.725
     1571011.547      382158.437
#Sta/Elev= 30
      10  879.89    60.2  855.34   100.4  836.43   130.5  822.94   160.6  809.85
   170.7   805.2   180.7   799.9   190.7  795.39   193.3  794.96   200.8  793.72
   208.3  794.01   210.8   794.1     251  798.39     261  799.97   291.1  806.45
   321.3  811.32   331.3  813.61   341.3  816.79   351.4  820.47   371.5  828.35
   381.5  832.49   401.2  838.93   430.7  849.09   450.4  855.17   489.8  865.71
   499.7  868.71   509.5  872.29   519.4  877.13   548.9  893.06   627.7  934.22
#Mann= 3 , 0 , 0
       0      .1       0   193.3    .045       0   208.3      .1       0
Bank Sta=193.3,208.3
XS Rating Curve= 0 ,0
Exp/Cntr=0.3,0.1

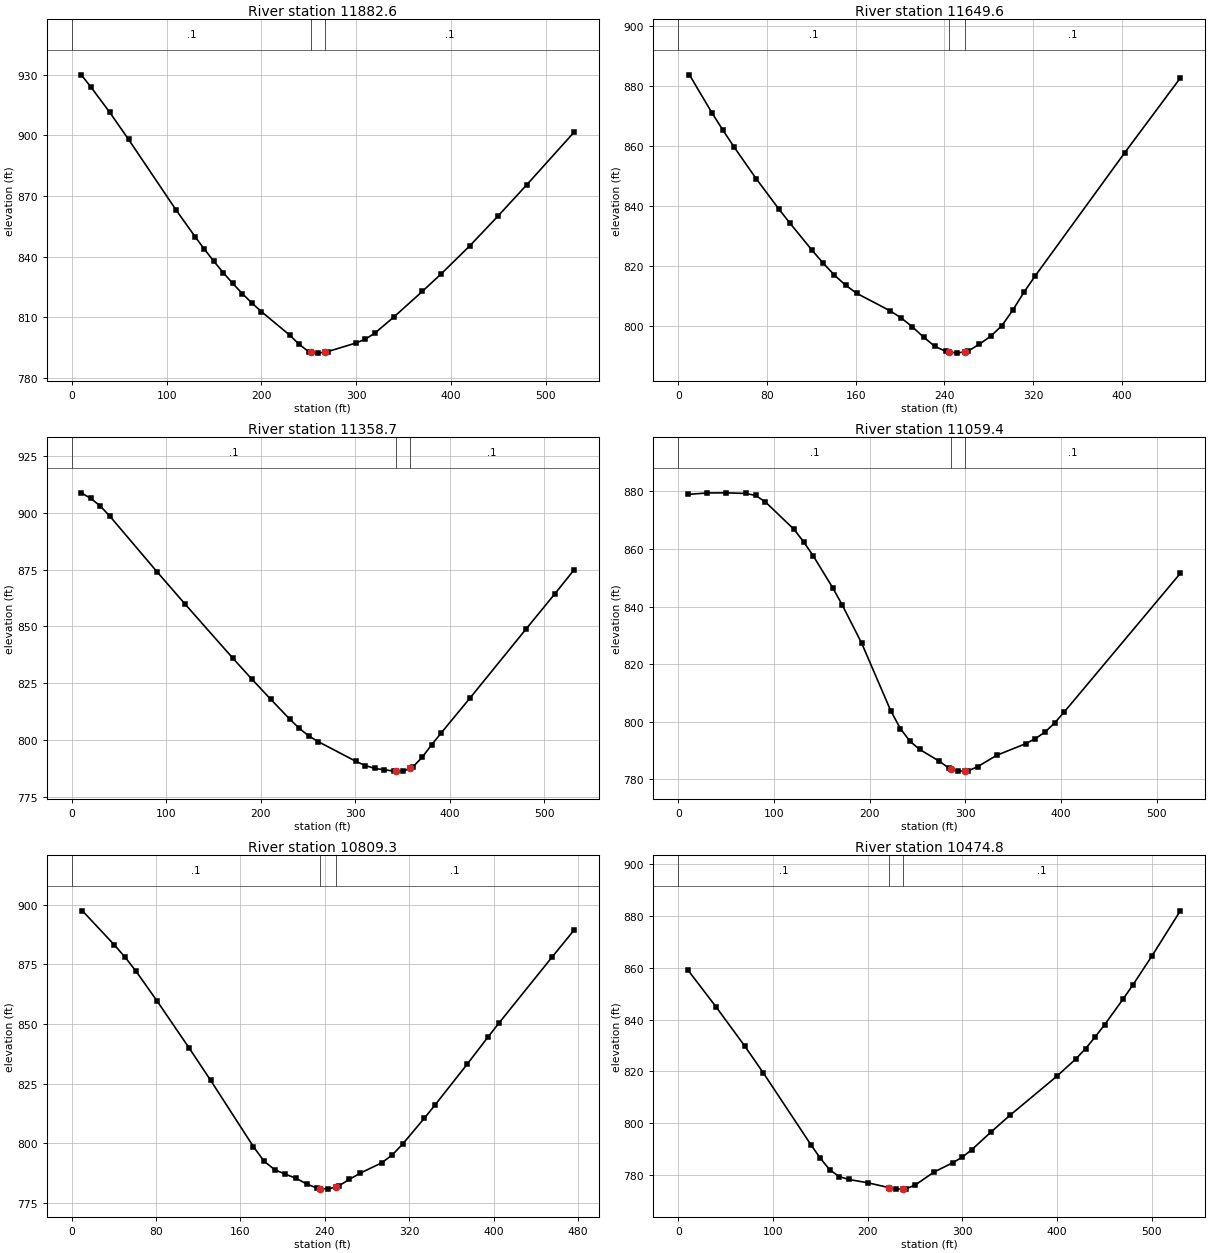
Type RM Length L Ch R = 1 ,11882.6 ,233.4,233,232.6
XS GIS Cut Line= 2
     1570336.202      382350.496     1570844.777      382497.497
#Sta/Elev= 30
      10  929.98      20  924.06      40  911.44    59.9     898   109.9  863.14
   129.9  849.96   139.8  843.69   149.8   837.7   159.8  832.04   169.8  826.72
   179.8  821.72   189.8  817.09   199.8  812.85   229.7  801.19   239.7  796.64
   249.7  793.01   252.2  792.82   259.7  792.25   267.2   792.8   269.7  792.98
   299.7  797.27   309.6  799.17   319.6  802.16   339.6  810.11   369.6  822.79
   389.6  831.51   419.5  845.26   449.5  860.13   479.5  875.43   529.4  901.46
#Mann= 3 , 0 , 0
       0      .1       0   252.2    .045       0   267.2      .1       0
Bank Sta=252.2,267.2
XS Rating Curve= 0 ,0
Exp/Cntr=0.3,0.1

Type RM Length L Ch R = 1 ,11649.6 ,291.7,290.9,290.1
XS GIS Cut Line= 2
     1570292.712      382583.758     1570729.764      382701.647
#Sta/Elev= 30
    10.1  883.83    30.2  871.24    40.2  865.39    50.3  859.74    70.4  849.06
    90.5  839.09   100.6  834.32   120.7  825.18   130.8  820.85   140.8  816.91
   150.9  813.53     161   810.8   191.1  804.95   201.2  802.54   211.2  799.58
   221.3  796.15   231.4   793.1   241.4  791.39     244  791.24   251.5  790.83
     259  791.35   261.5  791.53   271.6  793.83   281.7  796.48   291.7  799.95
   301.8  805.27   311.8  811.23   321.9  816.66   402.4  857.71   452.7  882.77
#Mann= 3 , 0 , 0
       0      .1       0     244    .045       0     259      .1       0
Bank Sta=244,259
XS Rating Curve= 0 ,0
Exp/Cntr=0.3,0.1

Type RM Length L Ch R = 1 ,11358.7 ,313.5,299.3,285
XS GIS Cut Line= 2
     1570111.566      382848.289     1570629.127      382969.053
#Sta/Elev= 29
      10  908.83    20.1  906.38    30.1  903.05    40.1  898.65    90.2   874.1
   120.3  859.68   170.5  836.05   190.5  826.88   210.6  817.97   230.6  809.27
   240.7  805.23   250.7  801.87   260.7  799.35   300.8  790.64   310.9  788.76
   320.9  787.53   330.9  786.88   340.9  786.39   343.5  786.38     351  786.33
   358.5  787.67     361  788.12     371  792.45     381  797.94   391.1  803.15
   421.2  818.31   481.3  849.08   511.4  864.37   531.5  874.82
#Mann= 3 , 0 , 0
       0      .1       0   343.5    .045       0   358.5      .1       0
Bank Sta=343.5,358.5
XS Rating Curve= 0 ,0
Exp/Cntr=0.3,0.1

Type RM Length L Ch R = 1 ,11059.4 ,259.7,250.1,240.5
XS GIS Cut Line= 2
      1570102.94      383328.471     1570585.997      383124.322
#Sta/Elev= 30
    10.1  878.92    30.3  879.41    50.4  879.46    70.6  879.24    80.7  878.55
    90.8  876.37     121  866.75   131.1  862.39   141.2  857.47   161.4  846.48
   171.4  840.46   191.6  827.26   221.9  803.86     232  797.63     242  793.25
   252.1  790.41   272.3  786.37   282.4  783.98     285  783.69   292.5  782.86
     300  782.92   302.6  782.93   312.6  784.38   332.8  788.38   363.1  792.41
   373.1  794.17   383.2  796.45   393.3  799.62   403.4  803.48   524.4  851.51
#Mann= 3 , 0 , 0
       0      .1       0     285    .045       0     300      .1       0
Bank Sta=285,300
XS Rating Curve= 0 ,0
Exp/Cntr=0.3,0.1

Type RM Length L Ch R = 1 ,10809.3 ,331.7,334.5,337.3
XS GIS Cut Line= 2
     1570393.349      383549.872     1570715.387      383199.081
#Sta/Elev= 30
    10.1  897.35    40.5  883.01    50.7  877.85    60.8  872.14    81.1  859.45
   111.5  839.77   131.7  826.35   172.2  798.61   182.4  792.47   192.5  788.89
   202.6  787.02   212.8  785.31   222.9  782.89     233  781.13   235.7  781.03
   243.2  780.77   250.7  781.78   253.3  782.14   263.4  784.88   273.6  787.47
   293.8  791.75     304   795.1   314.1  799.78   334.4  810.48   344.5  815.99
   374.9  833.04   395.1  844.66   405.3   850.4   455.9  878.17   476.2  889.15
#Mann= 3 , 0 , 0
       0      .1       0   235.7    .045       0   250.7      .1       0
Bank Sta=235.7,250.7
XS Rating Curve= 0 ,0
Exp/Cntr=0.3,0.1

Type RM Length L Ch R = 1 ,10474.8 ,371,387.6,404.2
XS GIS Cut Line= 2
      1570614.75      383756.897     1571017.298      383411.856
#Sta/Elev= 30
      10  859.28      40  844.91      70  829.92      90  819.35     140  791.73
   150.1  786.41   160.1  781.95   170.1  779.35   180.1  778.26   200.1  776.98
   222.6   775.1   230.1  774.52   237.6  774.61   240.1  774.64   250.1  776.06
   270.1  781.12   290.1  784.74   300.1  786.94   310.1  789.78   330.1  796.53
   350.1  802.98   400.1  818.23   420.1   824.9   430.2  828.83   440.2   833.3
   450.2  838.01   470.2  848.17   480.2  853.48   500.2  864.58   530.2  882.05
#Mann= 3 , 0 , 0
       0      .1       0   222.6    .045       0   237.6      .1       0
Bank Sta=222.6,237.6
XS Rating Curve= 0 ,0
Exp/Cntr=0.3,0.1

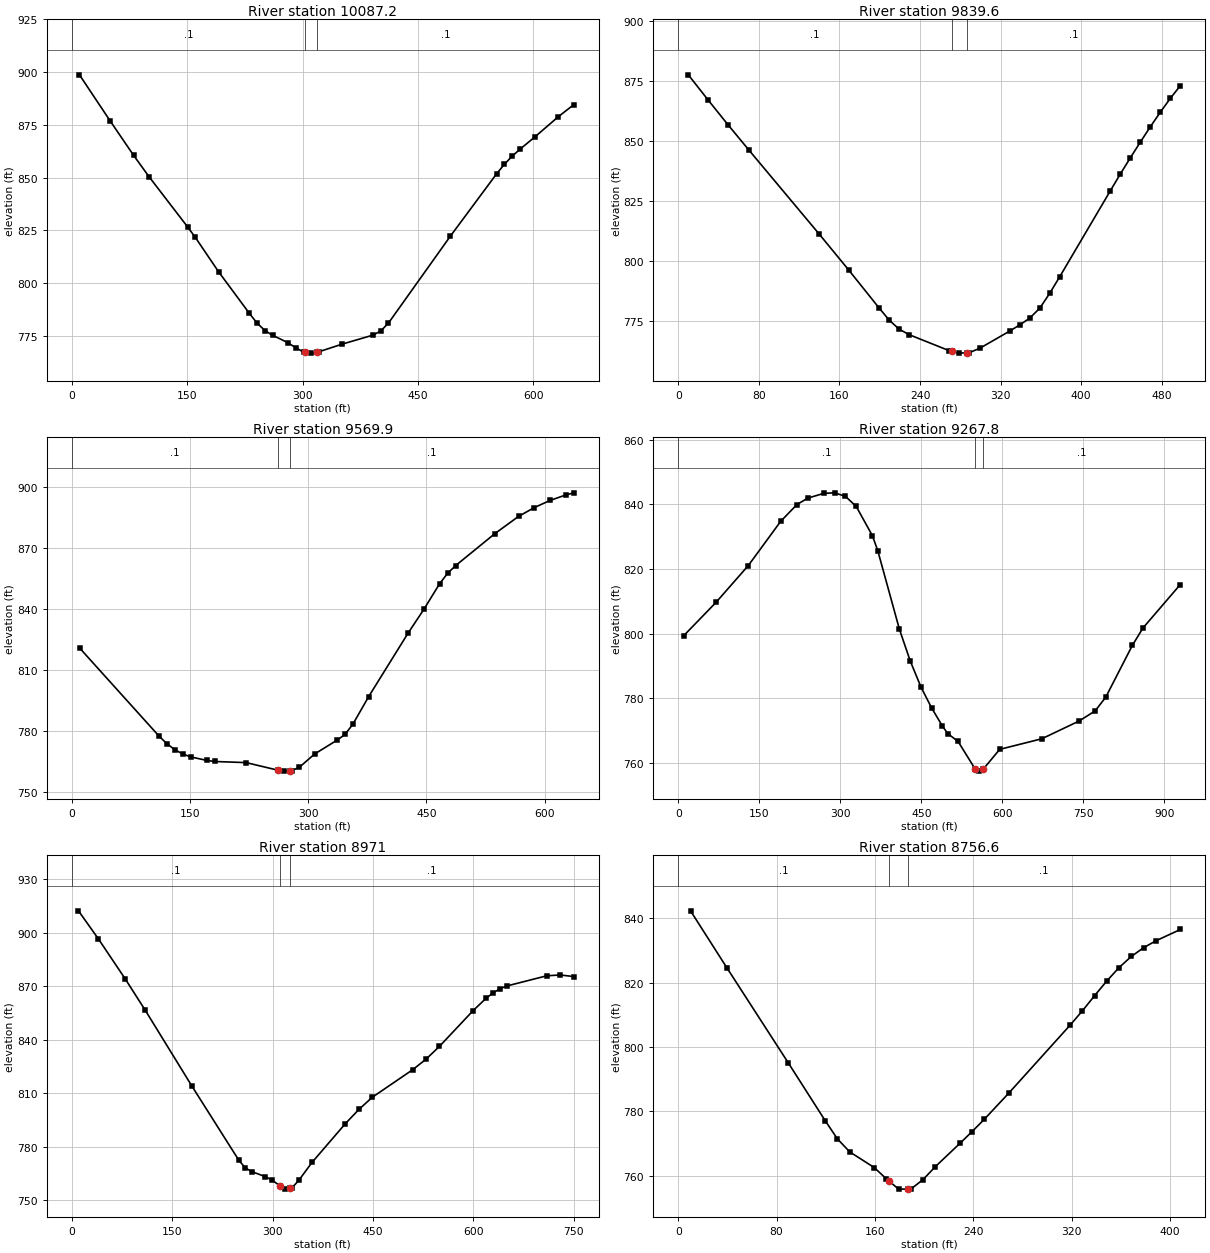
Type RM Length L Ch R = 1 ,10087.2 ,248.6,247.6,246.5
XS GIS Cut Line= 2
     1570683.758      383923.667     1571336.461       383915.04
#Sta/Elev= 30
      10  898.76    50.2  876.76    80.3  860.66   100.4   850.5   150.6  826.68
   160.7  821.68   190.8  805.47     231  785.66     241  781.05   251.1  777.57
   261.1  775.31   281.2  771.79   291.2  769.37   301.3  767.39   303.8  767.26
   311.3  766.86   318.8  767.35   321.4  767.52   351.5  771.12   391.7   775.4
   401.7  777.34   411.7  781.07   492.1  822.22   552.3  851.81   562.4  856.35
   572.4  860.13   582.5  863.42   602.5  869.44   632.7  878.94   652.8  884.65
#Mann= 3 , 0 , 0
       0      .1       0   303.8    .045       0   318.8      .1       0
Bank Sta=303.8,318.8
XS Rating Curve= 0 ,0
Exp/Cntr=0.3,0.1

Type RM Length L Ch R = 1 ,9839.6  ,267.9,269.8,271.6
XS GIS Cut Line= 2
     1570706.761      384182.447     1571204.195      384150.818
#Sta/Elev= 30
      10  877.48    29.9  866.87    49.8  856.49    69.8  846.34   139.6  811.36
   169.5  796.09   199.4  780.43   209.3  775.43   219.3   771.6   229.3  769.31
   269.2  762.62   271.6  762.38   279.1  761.64   286.6  761.83   289.1  761.89
   299.1   763.6     329  770.81   338.9  773.36   348.9   776.2   358.9  780.34
   368.8  786.57   378.8   793.5   428.7  829.05   438.6  836.03   448.6  842.81
   458.6   849.4   468.5  855.77   478.5   861.9   488.5  867.69   498.4  872.96
#Mann= 3 , 0 , 0
       0      .1       0   271.6    .045       0   286.6      .1       0
Bank Sta=271.6,286.6
XS Rating Curve= 0 ,0
Exp/Cntr=0.3,0.1

Type RM Length L Ch R = 1 ,9569.9  ,306.1,302.1,295.5
XS GIS Cut Line= 4
     1570755.642      384320.464     1570936.788      384429.726
     1571071.929      384432.602     1571350.837      384352.092
#Sta/Elev= 30
    10.1  820.82   110.8   777.6   120.9  773.82     131  770.91     141  768.81
   151.1  767.41   171.3   765.7   181.3  765.17   221.2  764.62     262  760.86
   269.5  760.44     277  760.62   279.1  760.67   288.8  762.36   308.1  768.84
   337.1  775.77   346.7  778.47   356.7  783.51   376.7  797.04   426.8  828.27
   446.8  839.92   466.8  852.51   476.9   857.6   486.9  861.31   536.9  877.08
   566.9  885.52     587  889.87     607  893.37     627  896.06     637  897.08
#Mann= 3 , 0 , 0
       0      .1       0     262    .045       0     277      .1       0
Bank Sta=262,277
XS Rating Curve= 0 ,0
Exp/Cntr=0.3,0.1

Type RM Length L Ch R = 1 ,9267.8  ,293.2,296.9,303
XS GIS Cut Line= 4
     1570545.742      384633.876     1571030.052      384703.818
     1571160.083      384668.124     1571408.344      384490.109
#Sta/Elev= 30
      10  799.32    69.9  809.64   129.8  821.05   189.7   834.7   219.7  839.88
   239.7  841.87   269.6  843.36   289.6  843.52   309.6  842.43   329.6  839.31
   359.5  830.28   369.5  825.63   409.4  801.43   429.4  791.62   449.4   783.5
   469.4  776.95   489.3  771.39     499  769.09   518.2  766.65   549.3  758.27
   556.8  757.48   564.3     758   595.3  764.21   673.4  767.49   742.4  772.98
     772   776.1   791.7  780.36     841  796.39   860.7  801.76   929.7  815.17
#Mann= 3 , 0 , 0
       0      .1       0   549.3    .045       0   564.3      .1       0
Bank Sta=549.3,564.3
XS Rating Curve= 0 ,0
Exp/Cntr=0.3,0.1

Type RM Length L Ch R = 1 ,8971    ,213.7,214.4,215.1
XS GIS Cut Line= 3
     1570764.268       384964.54        1571173.      384965.836
     1571483.103      384823.648
#Sta/Elev= 30
      10  912.22    39.9  896.41    79.8  874.09   109.7  856.52   179.4  813.99
   249.2  772.61   259.2  768.07   269.2  766.02   289.1  763.22   299.1  761.32
   311.5  757.92     319  756.23   326.5  756.81     329     757     339   761.1
   358.9  771.23   408.7  792.95   428.8  800.87   448.9  807.74   509.1  823.13
   529.1  829.06   549.2  836.25   599.4  856.28   619.4  863.41   629.5  866.26
   639.5  868.51   649.5  870.07   709.7  875.83   729.8  876.25   749.9  875.37
#Mann= 3 , 0 , 0
       0      .1       0   311.5    .045       0   326.5      .1       0
Bank Sta=311.5,326.5
XS Rating Curve= 0 ,0
Exp/Cntr=0.3,0.1

Type RM Length L Ch R = 1 ,8756.6  ,319.8,319.1,318.3
XS GIS Cut Line= 2
     1570913.786      385171.564     1571322.084      385183.066
#Sta/Elev= 27
      10  842.38    39.8  824.52    89.7  794.97   119.5  777.12   129.5  771.42
   139.5  767.38   159.4  762.51   169.4  758.96   171.8  758.19   179.3  755.78
   186.8   755.8   189.3  755.81   199.2  758.76   209.2  762.78   229.1  769.99
   239.1  773.69   249.1  777.55     269  785.68   318.8  806.79   328.8  811.25
   338.7  815.95   348.7  820.56   358.6   824.7   368.6  828.17   378.6   830.9
   388.5  833.02   408.5  836.57
#Mann= 3 , 0 , 0
       0      .1       0   171.8    .045       0   186.8      .1       0
Bank Sta=171.8,186.8
XS Rating Curve= 0 ,0
Exp/Cntr=0.3,0.1

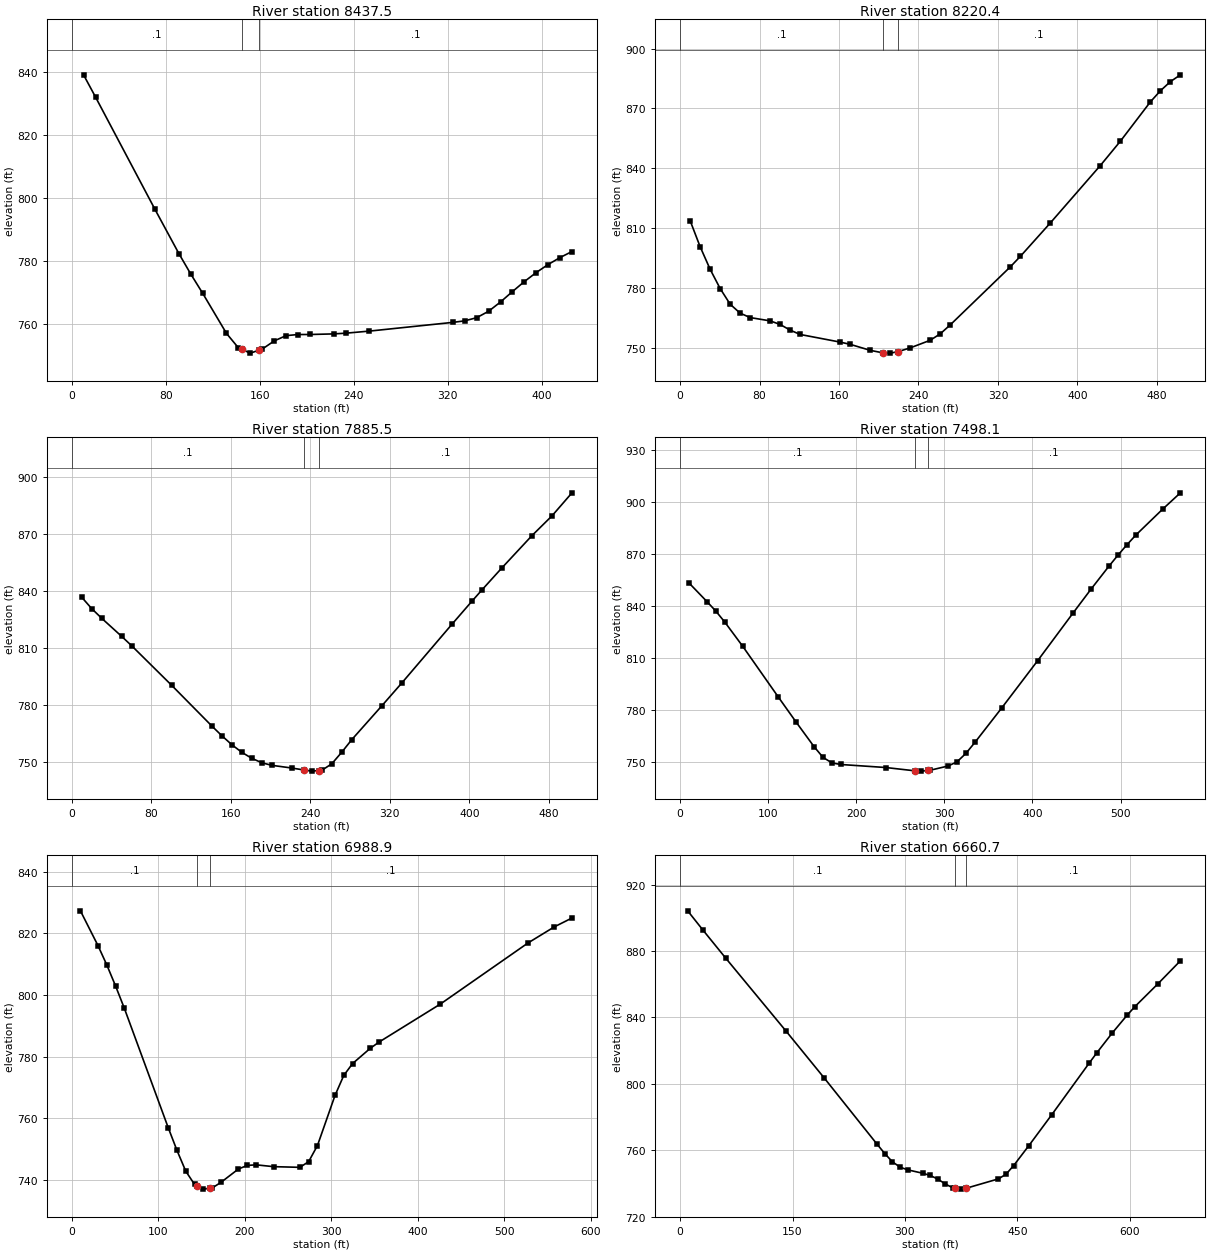
Type RM Length L Ch R = 1 ,8437.5  ,210.5,217.1,223.9
XS GIS Cut Line= 2
     1570885.032      385487.852     1571310.583      385484.976
#Sta/Elev= 30
    10.1  839.03    20.3  831.96    70.9  796.25    91.2  782.23   101.3  775.73
   111.5  769.58   131.7  756.86   141.9  752.25   144.5  751.82     152   750.6
   159.5  751.55   162.1  751.88   172.3  754.48   182.4  756.16   192.5  756.51
   202.6  756.52   222.9  756.71     233  756.93   253.3   757.6   324.2  760.37
   334.4  760.86   344.5  761.86   354.6  763.89   364.8  766.85   374.9  770.14
     385  773.31   395.2  776.21   405.3  778.76   415.4  780.96   425.6  782.89
#Mann= 3 , 0 , 0
       0      .1       0   144.5    .045       0   159.5      .1       0
Bank Sta=144.5,159.5
XS Rating Curve= 0 ,0
Exp/Cntr=0.3,0.1

Type RM Length L Ch R = 1 ,8220.4  ,340.8,334.9,328.7
XS GIS Cut Line= 2
     1570828.604      385635.572     1571310.223      385782.934
#Sta/Elev= 30
    10.1  813.79    20.1  800.81    30.2  789.46    40.3  779.79    50.4  771.92
    60.4  767.45    70.5  765.23    90.7  763.57   100.7  761.77   110.8  758.94
   120.9  756.76   161.2  752.93   171.2  751.82   191.4  748.81     204  747.57
   211.5  747.41     219  748.09   231.7  750.04   251.8  753.85   261.9  757.07
     272  761.57   332.4  790.61   342.5  795.86   372.7  812.62   423.1  841.42
   443.2  853.56   473.4  873.26   483.5  878.84   493.6  883.44   503.7  886.86
#Mann= 3 , 0 , 0
       0      .1       0     204    .045       0     219      .1       0
Bank Sta=204,219
XS Rating Curve= 0 ,0
Exp/Cntr=0.3,0.1

Type RM Length L Ch R = 1 ,7885.5  ,387.6,387.4,387.3
XS GIS Cut Line= 2
     1570763.908      385998.584     1571267.093      386009.367
#Sta/Elev= 30
    10.1  836.88    20.1  830.89    30.2  825.79    50.3  816.24    60.4  811.28
   100.7  790.41   140.9  769.08     151  763.94   161.1  759.19   171.1  755.19
   181.2  752.01   191.3  749.66   201.3  748.32   221.5  746.89   234.1  745.82
   241.6  745.26   249.1  745.59   251.7  745.71   261.7  749.14   271.8  755.29
   281.8  761.86     312  779.66   332.2  791.75   382.5   822.6   402.6  834.74
   412.7  840.71   432.8  852.33     463  869.31   483.2  879.74   503.3  891.87
#Mann= 3 , 0 , 0
       0      .1       0   234.1    .045       0   249.1      .1       0
Bank Sta=234.1,249.1
XS Rating Curve= 0 ,0
Exp/Cntr=0.3,0.1

Type RM Length L Ch R = 1 ,7498.1  ,516.6,509.2,501.7
XS GIS Cut Line= 2
     1570677.648      386379.567     1571245.528      386386.755
#Sta/Elev= 30
    10.1  853.25    30.4  842.54    40.6  836.97    50.7  830.68      71  816.74
   111.6  787.28   131.8  772.82   152.1  758.67   162.3  752.49   172.4  749.31
   182.5   748.4   233.3  746.66   266.3  744.76   273.8  744.57   281.3  744.96
     284   745.1   304.2  747.53   314.4  749.96   324.5  754.86   334.7  761.19
   365.1  781.07   405.7  808.25   446.2  835.99   466.5  849.71   486.8  862.95
   496.9  869.24   507.1  875.25   517.2  880.86   547.6   895.8   567.9  905.31
#Mann= 3 , 0 , 0
       0      .1       0   266.3    .045       0   281.3      .1       0
Bank Sta=266.3,281.3
XS Rating Curve= 0 ,0
Exp/Cntr=0.3,0.1

Type RM Length L Ch R = 1 ,6988.9  ,311.4,328.2,345.1
XS GIS Cut Line= 2
      1570713.59      386907.911     1571263.499      386728.202
#Sta/Elev= 30
    10.1  827.33    30.4  816.04    40.6  809.76    50.7  802.95    60.9  795.66
   111.6   756.9   121.8  749.47   131.9  742.76   142.1  738.43   144.7  738.04
   152.2  736.92   159.7  737.19   162.4  737.29   172.5  739.09   192.8  743.46
     203  744.61   213.1  744.82   233.4  744.22   263.9     744     274  745.85
   284.2  751.09   304.5  767.36   314.6  773.85   324.8  777.71   345.1  782.63
   355.2  784.66   426.3  797.04   527.8  816.92   558.2  822.14   578.5     825
#Mann= 3 , 0 , 0
       0      .1       0   144.7    .045       0   159.7      .1       0
Bank Sta=144.7,159.7
XS Rating Curve= 0 ,0
Exp/Cntr=0.3,0.1

Type RM Length L Ch R = 1 ,6660.7  ,368,367.5,367
XS GIS Cut Line= 2
     1570577.011      387015.736     1571184.427      387292.487
#Sta/Elev= 30
    10.1  904.24    30.3  892.75    60.7  875.84   141.6  831.67   192.2  803.62
     263  763.56   273.1  758.04   283.2  753.12   293.3  749.91   303.4  748.27
   323.6  746.21   333.7  744.88   343.9  742.65     354  739.69   364.1  737.35
   366.7  737.16   374.2  736.63   381.7  737.16   424.8  742.82   434.9  745.63
     445   750.8   465.2  762.75   495.6  781.28   546.1  812.72   556.2  818.85
   576.5  830.63   596.7  841.54   606.8  846.55   637.2  860.15   667.5  874.15
#Mann= 3 , 0 , 0
       0      .1       0   366.7    .045       0   381.7      .1       0
Bank Sta=366.7,381.7
XS Rating Curve= 0 ,0
Exp/Cntr=0.3,0.1

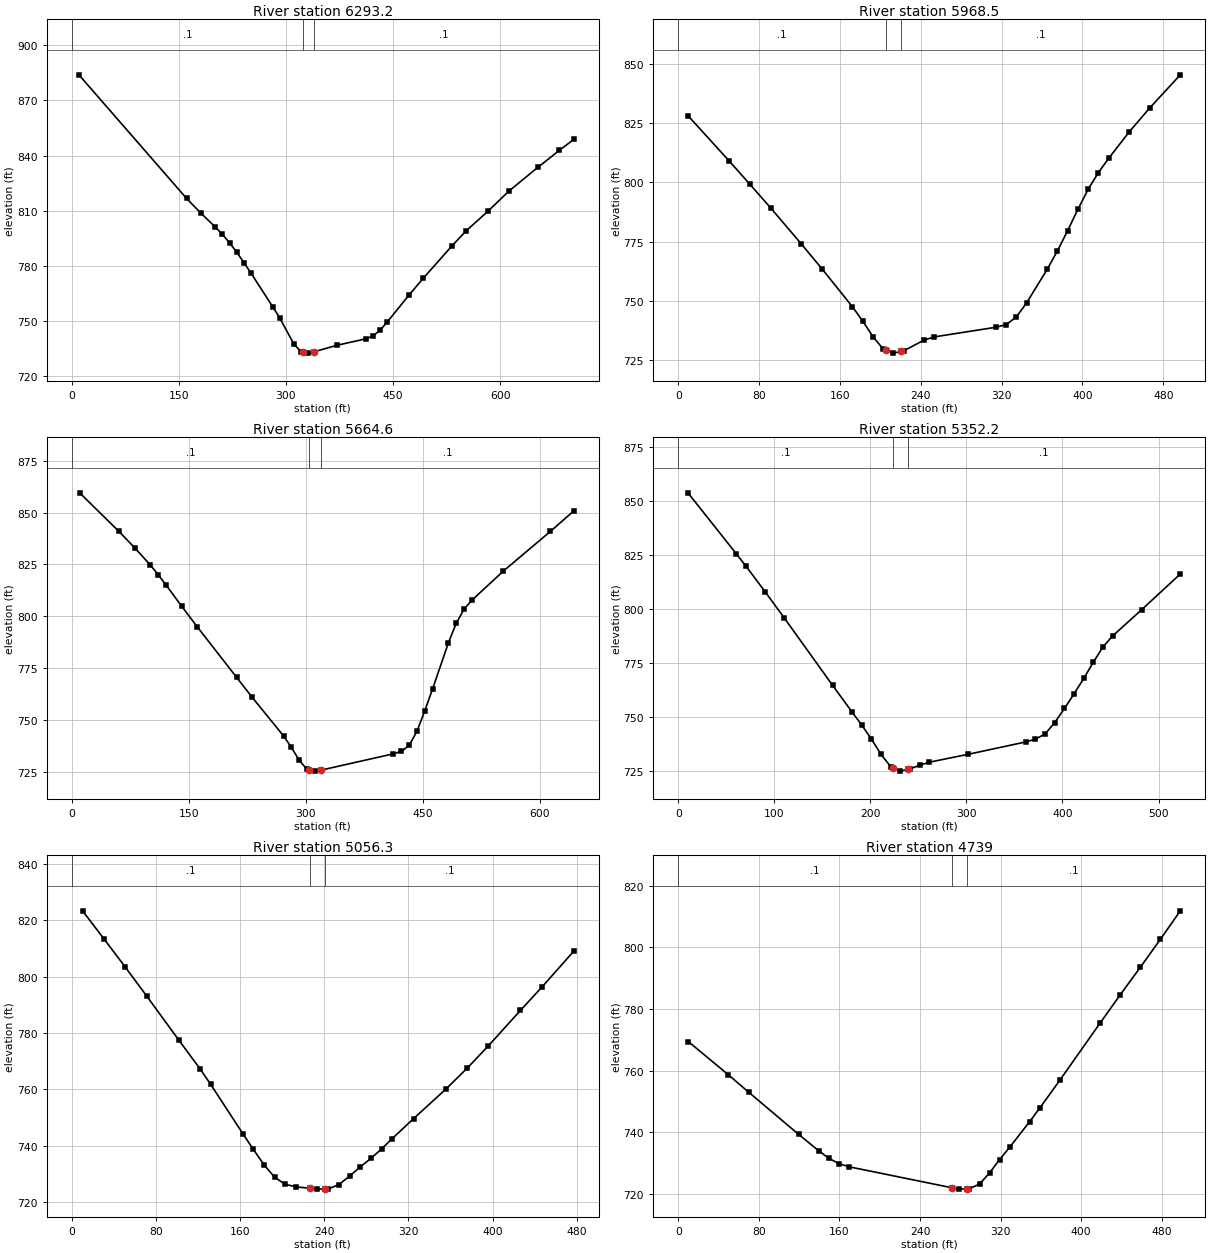
Type RM Length L Ch R = 1 ,6293.2  ,326.2,324.7,323.2
XS GIS Cut Line= 2
     1570390.114      387324.835     1571033.472      387608.775
#Sta/Elev= 30
      10  883.92   160.7  816.76   180.8  808.71   200.9  801.22     211  797.14
     221  792.59   231.1  787.45   241.1  781.84   251.2  776.01   281.3   757.9
   291.3  751.68   311.4  737.32   321.5  733.27     324  733.11   331.5   732.6
     339  733.29   371.7   736.9   411.9  740.37   421.9  741.91     432  745.15
     442  749.62   472.2  764.12   492.3   773.3   532.4  790.88   552.5  799.14
   582.7  809.68   612.8  820.88     653  833.68   683.1  842.91   703.2  848.83
#Mann= 3 , 0 , 0
       0      .1       0     324    .045       0     339      .1       0
Bank Sta=324,339
XS Rating Curve= 0 ,0
Exp/Cntr=0.3,0.1

Type RM Length L Ch R = 1 ,5968.5  ,302.5,303.9,305.3
XS GIS Cut Line= 2
     1570336.202      387669.876     1570803.444      387838.802
#Sta/Elev= 30
    10.1   827.9    50.7  808.87      71  799.12    91.3  789.27   121.7  774.03
     142  763.61   172.4  747.45   182.5  741.45   192.7  734.85   202.8  729.62
   205.4  729.18   212.9   727.9   220.4  728.61   223.1  728.86   243.4  733.44
   253.5  734.76   314.3  738.82   324.5  739.93   334.6  743.17   344.7  749.11
     365  763.22   375.2  771.05   385.3  779.58   395.4  788.53   405.6  797.05
   415.7  804.09   425.9  810.11   446.1   821.2   466.4  831.33   496.8  845.37
#Mann= 3 , 0 , 0
       0      .1       0   205.4    .045       0   220.4      .1       0
Bank Sta=205.4,220.4
XS Rating Curve= 0 ,0
Exp/Cntr=0.3,0.1

Type RM Length L Ch R = 1 ,5664.6  ,307.7,312.4,317.2
XS GIS Cut Line= 2
      1570170.87      387907.091     1570760.314      388165.872
#Sta/Elev= 30
    10.1  859.58    60.4  840.97    80.5  833.12   100.6  824.81   110.6  820.16
   120.7  815.18   140.8  804.91   160.9  794.91   211.2   770.6   231.3   760.9
   271.6  742.26   281.6  736.72   291.7  730.47   301.8   726.1   304.3   725.9
   311.8   725.3   319.3  725.75   412.4  733.66   422.5  734.79   432.5  737.67
   442.6  744.57   452.6  754.41   462.7  765.06   482.8  787.15   492.9  796.63
   502.9   803.4     513  807.78   553.2  821.78   613.6  840.96   643.7  850.87
#Mann= 3 , 0 , 0
       0      .1       0   304.3    .045       0   319.3      .1       0
Bank Sta=304.3,319.3
XS Rating Curve= 0 ,0
Exp/Cntr=0.3,0.1

Type RM Length L Ch R = 1 ,5352.2  ,294.3,295.8,297.4
XS GIS Cut Line= 2
     1570073.827      388140.713     1570497.939      388446.218
#Sta/Elev= 30
    10.1     854    60.3  825.86    70.4  820.09    90.5  808.17   110.6  795.92
   160.8  764.77   180.9  752.52     191  746.48     201  740.02   211.1   732.9
   221.1  727.21   223.7  726.67   231.2  725.11   238.7  725.87   241.2  726.12
   251.3  727.84   261.3  729.23   301.6  732.89   361.9  738.64   371.9  739.93
     382  742.34     392  747.62   402.1  754.12   412.1  760.93   422.2  768.05
   432.2   775.6   442.3   782.7   452.3  787.74   482.5  799.89   522.7  816.41
#Mann= 3 , 0 , 0
       0      .1       0   223.7    .045       0   238.7      .1       0
Bank Sta=223.7,238.7
XS Rating Curve= 0 ,0
Exp/Cntr=0.3,0.1

Type RM Length L Ch R = 1 ,5056.3  ,320.4,317.3,314.3
XS GIS Cut Line= 2
       1569904.9      388359.958     1570271.506      388665.462
#Sta/Elev= 30
    10.2  823.31    30.5  813.42    50.8  803.38    71.1  793.15   101.5  777.58
   121.8  767.34     132  761.79   162.5  744.32   172.6  738.69   182.8  733.22
   192.9  728.76   203.1  726.29   213.2  725.42     226  724.94   233.5  724.61
     241  724.64   243.7  724.66   253.8  726.21     264  729.21   274.1  732.44
   284.3  735.51   294.5  738.87   304.6  742.55   324.9  749.62   355.4  760.03
   375.7  767.46     396  775.44   426.4  787.97   446.8  796.24   477.2  809.03
#Mann= 3 , 0 , 0
       0      .1       0     226    .045       0     241      .1       0
Bank Sta=226,241
XS Rating Curve= 0 ,0
Exp/Cntr=0.3,0.1

Type RM Length L Ch R = 1 ,4739    ,580.8,560.9,541.1
XS GIS Cut Line= 2
     1569660.497      388597.173     1570077.421       388870.33
#Sta/Elev= 24
      10  769.48    49.8  758.69    69.8  753.09   119.6  739.35   139.6  734.02
   149.5  731.61   159.5   729.9   169.5  728.87   271.6  722.07   279.1  721.62
   286.6  721.75   289.1  721.79   299.1  723.27     309  726.86     319  731.22
     329  735.19   348.9  743.54   358.9  747.91   378.8  756.94   418.7  775.44
   438.6  784.57   458.6  793.51   478.5  802.58   498.4  811.87
#Mann= 3 , 0 , 0
       0      .1       0   271.6    .045       0   286.6      .1       0
Bank Sta=271.6,286.6
XS Rating Curve= 0 ,0
Exp/Cntr=0.3,0.1

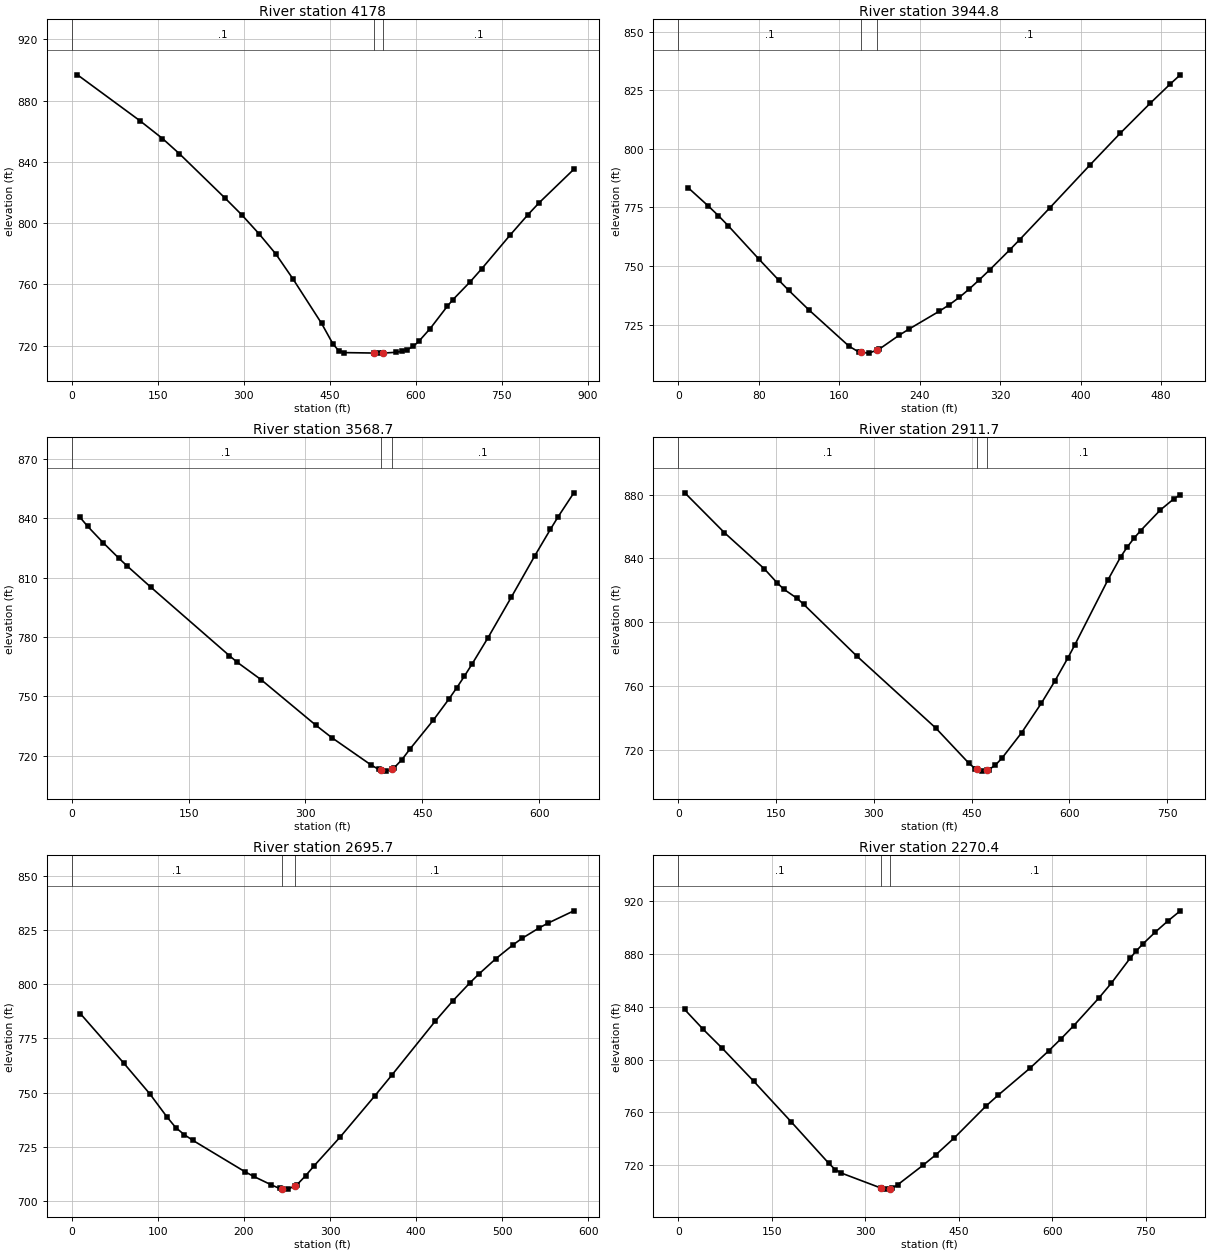
Type RM Length L Ch R = 1 ,4178    ,233.1,233.2,233.4
XS GIS Cut Line= 4
     1569247.166      389226.154      1569602.99      389233.342
     1569933.654      389121.923     1570091.798      389057.228
#Sta/Elev= 30
     9.9  896.91   118.6     867   158.2  855.31   187.8  845.35   266.9  816.55
   296.6  805.43   326.2  793.25   355.9   779.9   385.8  763.61   435.7  734.56
   455.6  721.09   465.6  716.72   475.5  715.48   527.8  715.19   535.3  715.14
   542.8  715.17   565.3  715.67   575.2  716.31   585.2  717.43   595.2  719.47
   605.1  722.77   625.1  731.16     655  745.75   664.9  750.11   694.9  761.73
   714.9  770.19   765.1  792.49   795.3  805.42   815.4  813.44   875.7  835.22
#Mann= 3 , 0 , 0
       0      .1       0   527.8    .045       0   542.8      .1       0
Bank Sta=527.8,542.8
XS Rating Curve= 0 ,0
Exp/Cntr=0.3,0.1

Type RM Length L Ch R = 1 ,3944.8  ,361.3,376.1,390.9
XS GIS Cut Line= 2
     1569656.902      389456.181     1570127.739      389290.849
#Sta/Elev= 30
      10  783.36    29.9  775.61    39.9  771.51    49.9  767.11    79.8  753.16
    99.8  744.04   109.8  739.67   129.7  731.39   169.7  715.87   179.6  713.34
   182.1  713.23   189.6   712.9   197.1  714.14   199.6  714.55   219.6  720.54
   229.5  723.19   259.5  730.78   269.5  733.56   279.5  736.72   289.4  740.31
   299.4  744.23   309.4  748.34   329.4  756.89   339.3  761.26   369.3  774.84
   409.2  793.11   439.1  806.56   469.1  819.44     489  827.64     499  831.55
#Mann= 3 , 0 , 0
       0      .1       0   182.1    .045       0   197.1      .1       0
Bank Sta=182.1,197.1
XS Rating Curve= 0 ,0
Exp/Cntr=0.3,0.1

Type RM Length L Ch R = 1 ,3568.7  ,692.5,657,621.5
XS GIS Cut Line= 3
     1569484.382      389747.309      1569786.56      389717.762
     1570109.769      389826.381
#Sta/Elev= 30
    10.1  840.79    20.2   836.1    40.5  827.65    60.7  819.79    70.8  816.06
   101.2  805.34   202.4  770.58   212.5  767.24   242.9   758.5   313.6  735.34
   333.7  729.17   383.8  715.43   393.9  713.09   396.4  712.86   403.9  712.19
   411.4  713.45   413.9  713.87     424  718.06     434  723.27   464.1  737.93
   484.1  748.59   494.2  754.31   504.2  760.29   514.2  766.53   534.3   779.6
   564.4  800.23   594.4  821.07   614.5  834.49   624.5  840.91   644.6  852.96
#Mann= 3 , 0 , 0
       0      .1       0   396.4    .045       0   411.4      .1       0
Bank Sta=396.4,411.4
XS Rating Curve= 0 ,0
Exp/Cntr=0.3,0.1

Type RM Length L Ch R = 1 ,2911.7  ,207.6,216,224.5
XS GIS Cut Line= 3
     1569678.753      390437.915     1570032.136      390261.623
     1570160.087      389909.047
#Sta/Elev= 30
    10.1  881.09    70.9  856.09   131.6  833.65   151.9   824.6     162  820.67
   182.3  814.97   192.4  811.21   273.4  778.99   394.9  733.74   445.6  711.73
   455.7  708.16   458.4  707.78   465.9  706.72   473.4  707.35     476  707.57
   486.1  710.41   496.3  714.75   526.7  730.82   557.1  749.41   577.4  763.03
   597.7  777.73   607.8  785.49   658.5  826.16   678.8  841.16   688.9  847.28
     699  852.65   709.2  857.44   739.6  870.42   759.9  877.24     770  879.88
#Mann= 3 , 0 , 0
       0      .1       0   458.4    .045       0   473.4      .1       0
Bank Sta=458.4,473.4
XS Rating Curve= 0 ,0
Exp/Cntr=0.3,0.1

Type RM Length L Ch R = 1 ,2695.7  ,405.4,425.2,445
XS GIS Cut Line= 2
     1570088.203      390466.145      1570472.78      390027.655
#Sta/Elev= 30
    10.1  786.31    60.3  763.59    90.5  749.45   110.6  738.72   120.7  733.84
   130.7  730.55   140.8   727.9   201.1  713.48   211.2  711.33   231.3   707.5
   241.3  705.75   243.9  705.67   251.4  705.44   258.9  706.91   261.5  707.42
   271.5  711.56   281.6  716.24   311.7  729.44     352  748.44   372.1  758.17
   422.3  782.95   442.5   792.2   462.6  800.62   472.6  804.52   492.7  811.74
   512.9  818.19   522.9  821.06     543  825.93   553.1  828.09   583.2  833.78
#Mann= 3 , 0 , 0
       0      .1       0   243.9    .045       0   258.9      .1       0
Bank Sta=243.9,258.9
XS Rating Curve= 0 ,0
Exp/Cntr=0.3,0.1

Type RM Length L Ch R = 1 ,2270.4  ,136.3,135.5,134.7
XS GIS Cut Line= 2
     1570070.233      390638.541     1570875.328      390660.106
#Sta/Elev= 30
    10.1  837.94    40.3  822.73    70.5  808.59   120.8  783.74   181.2  752.92
   241.6  721.51   251.7  716.88   261.7   714.2   324.7  702.96   332.2  702.05
   339.7  702.44   342.3  702.58   352.4  705.48   392.6  720.08   412.8  727.84
     443  740.86   493.3  764.69   513.4  773.16   563.8  793.32     594  806.46
   614.1  815.73   634.2   825.5   674.5   846.4   694.6  857.65   724.8  876.56
   734.9  882.22     745  887.23   765.1  896.31   785.2  904.67   805.4  912.44
#Mann= 3 , 0 , 0
       0      .1       0   324.7    .045       0   339.7      .1       0
Bank Sta=324.7,339.7
XS Rating Curve= 0 ,0
Exp/Cntr=0.3,0.1