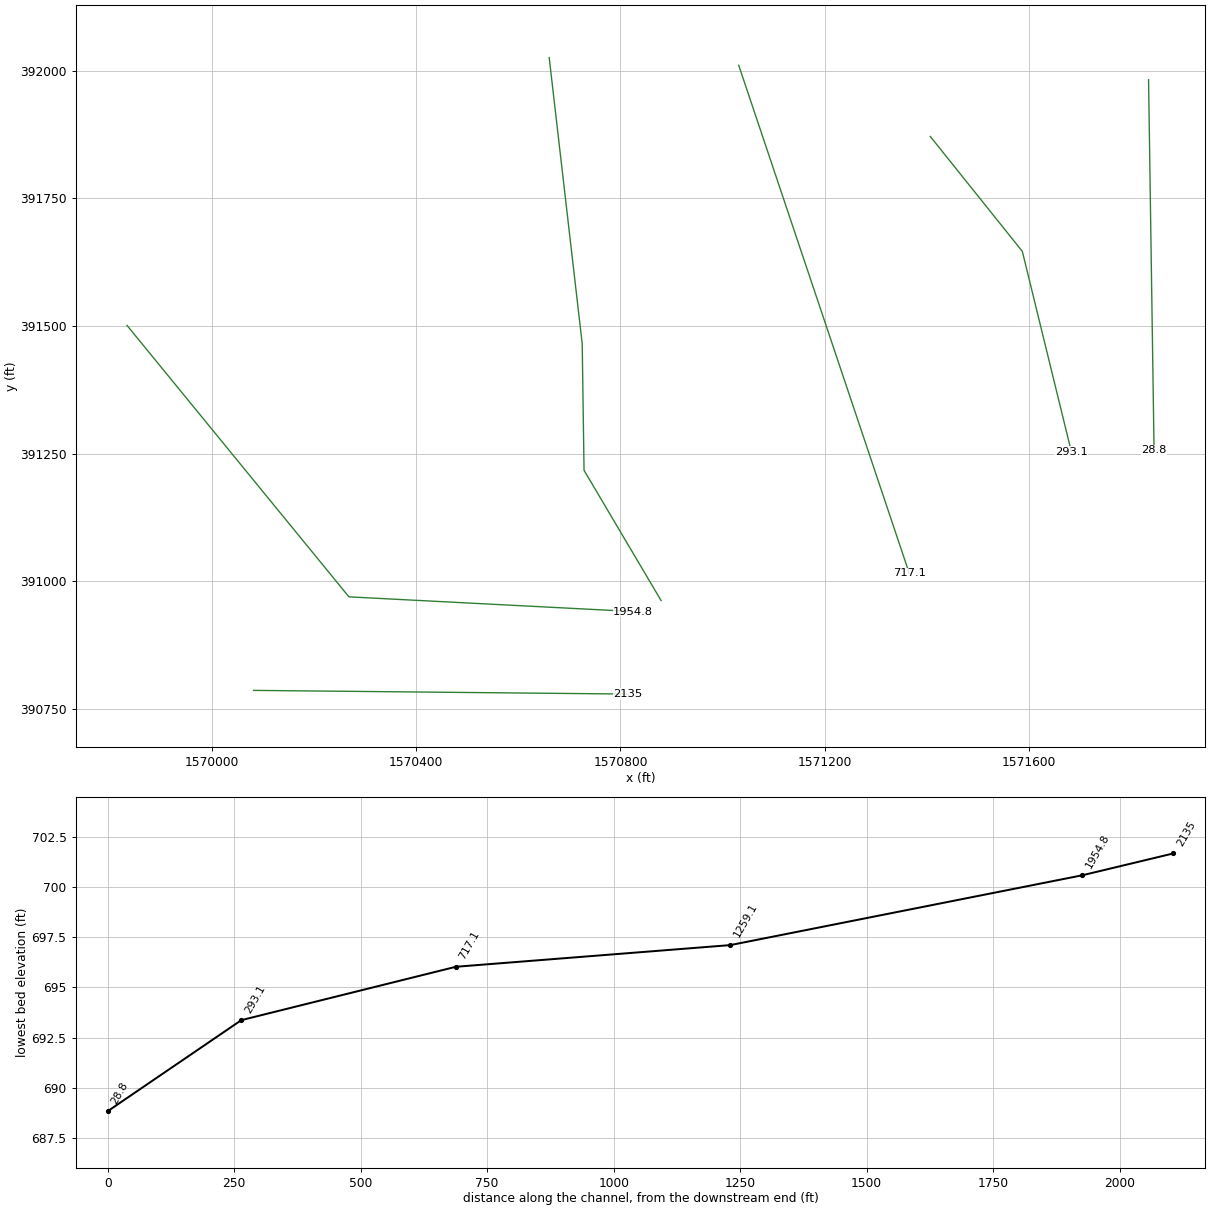
HEC-RAS study RFRICHCR.prj: RFRICHCR

--- RFRICHCR.g01 (geometry) --- (continued)

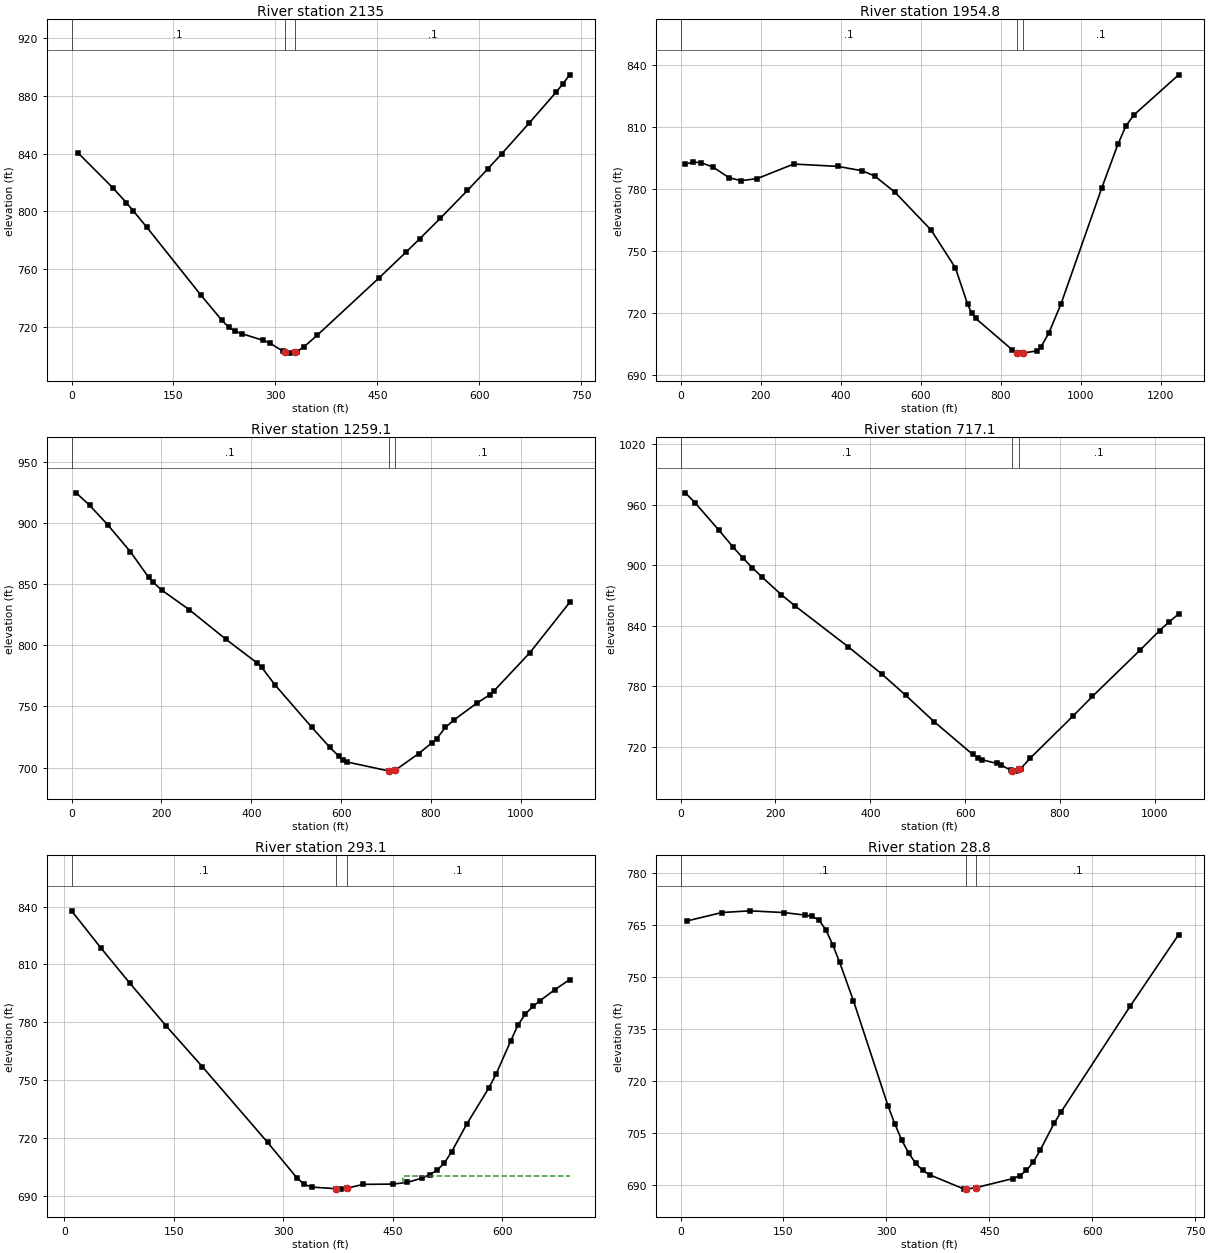
Type RM Length L Ch R = 1 ,2135    ,181.1,180.1,179.2
XS GIS Cut Line= 2
     1570081.015      390786.026     1570814.227      390778.838
#Sta/Elev= 30
      10  840.38    60.3   816.6    80.4  806.17    90.4  800.64   110.5  789.16
   190.8  741.67     221  724.58     231  719.79   241.1   716.8   251.1  715.09
   281.2  710.68   291.3  708.77   311.4  702.95   313.9  702.63   321.4  701.68
   328.9  702.46   331.5  702.73   341.5  705.85   361.6  714.11     452  753.65
   492.2  771.74   512.3  780.98   542.4  795.11   582.6  814.55   612.7  829.58
   632.8  839.87     673  861.05   713.2  882.79   723.2  888.62   733.2  894.79
#Mann= 3 , 0 , 0
       0      .1       0   313.9    .045       0   328.9      .1       0
Bank Sta=313.9,328.9
XS Rating Curve= 0 ,0
Exp/Cntr=0.3,0.1

Type RM Length L Ch R = 1 ,1954.8  ,730.1,695.7,661.3
XS GIS Cut Line= 3
     1569833.017      391501.267     1570267.912      390969.329
      1570825.01      390940.576
#Sta/Elev= 30
    10.1  791.92    30.3  793.02    50.5   792.8    80.8  790.67   121.3  785.47
   151.6  784.03     192  785.08   282.9   792.1   394.1  790.94   454.7   788.8
     485  786.32   535.5  778.53   626.5   760.1   687.1  741.79   717.5  724.19
   727.7  719.87   737.8  717.37   829.1  702.16   841.9  700.82   849.4  700.59
   856.9  700.68   889.9  701.65   900.1  703.32   920.4  710.34   950.8   724.4
  1052.2  780.26  1092.8  801.56  1113.1   810.6  1133.4  815.93  1244.9  835.27
#Mann= 3 , 0 , 0
       0      .1       0   841.9    .045       0   856.9      .1       0
Bank Sta=841.9,856.9
XS Rating Curve= 0 ,0
Exp/Cntr=0.3,0.1

Type RM Length L Ch R = 1 ,1259.1  ,535.1,542.1,549
XS GIS Cut Line= 4
     1570660.382      392026.017     1570725.078      391465.325
     1570728.672      391217.327     1570879.627      390962.141
#Sta/Elev= 30
    10.1  924.65    40.3  914.42    80.6  898.47     131  876.45   171.3  855.66
   181.4  851.52   201.6  844.88     262  829.08   342.7  805.16   413.2  785.48
   423.3  781.92   453.5   767.3   534.2  733.17   574.3  716.76   594.2  709.56
   604.1   706.5     614  704.52   705.7  697.28   713.2  697.11   720.7  697.95
   772.8  711.49   802.5  720.36   812.4  723.53   832.2  732.91     852  739.17
   901.4  752.51     931  759.62   940.9  762.97    1020  793.89  1108.9  835.15
#Mann= 3 , 0 , 0
       0      .1       0   705.7    .045       0   720.7      .1       0
Bank Sta=705.7,720.7
XS Rating Curve= 0 ,0
Exp/Cntr=0.3,0.1

Type RM Length L Ch R = 1 ,717.1   ,427.5,424,420.6
XS GIS Cut Line= 2
     1571031.753       392011.18     1571366.011      391015.593
#Sta/Elev= 30
    10.1  971.59    30.3  961.95    80.8  934.68   111.1  917.73   131.3  907.14
   151.5  897.41   171.7  888.25   212.1   870.9   242.4  859.29   353.4  819.19
   424.1  792.31   474.6  771.18   535.2  744.75     616  712.55   626.1  709.23
   636.2  707.22   666.5  703.69   676.6  701.78   696.8  696.81   699.4  696.61
   706.9  696.03   714.4   697.8     717  698.42   737.2  708.87     828  750.83
   868.4  770.03   969.4  816.14  1009.8  835.16    1030  843.73  1050.2  851.73
#Mann= 3 , 0 , 0
       0      .1       0   699.4    .045       0   714.4      .1       0
Bank Sta=699.4,714.4
XS Rating Curve= 0 ,0
Exp/Cntr=0.3,0.1

Type RM Length L Ch R = 1 ,293.1   ,267.9,264.2,260.6
XS GIS Cut Line= 3
     1571407.266      391871.467     1571587.597       391646.38
     1571683.675      391253.714
#Sta/Elev= 30
     9.9  837.76    49.7  818.68    89.5  800.33   139.2  778.18     189  756.94
   278.5  717.64   318.7  699.23   328.8  695.83   338.9  694.44   371.9   693.6
   379.4  693.37   386.9   693.8   409.7  695.84   450.1  695.99   470.3  696.87
   490.5  699.16   500.6  700.84   510.8  703.16   520.9  706.97     531  712.86
   551.2  726.92   581.5  745.67   591.6  752.94   611.8  770.28   621.9  778.59
     632  784.34   642.1  788.13   652.2   791.2   672.5  796.94   692.7  802.08
#Mann= 3 , 0 , 0
     9.9      .1       0   371.9    .045       0   386.9      .1       0
#XS Ineff= 2 , 0
                          463.74          699.96
Permanent Ineff=
       F       F
Bank Sta=371.9,386.9
XS Rating Curve= 0 ,0
Exp/Cntr=0.3,0.1

Type RM Length L Ch R = 1 ,28.8    ,18.5,28.8,39
XS GIS Cut Line= 2
     1571834.973      391982.887     1571845.755      391256.863
#Sta/Elev= 30
    10.1  766.18    60.5  768.57   100.8  769.06   151.3  768.55   181.5  767.82
   191.6   767.5   201.7  766.42   211.8  763.59   221.9  759.26   231.9  754.23
   252.1  743.11   302.5  712.81   312.6  707.49   322.7  702.88   332.8  699.12
   342.9  696.25     353  694.22   363.1  692.96   413.5  688.83   416.1  688.83
   431.1  689.28   484.1  691.86   494.2  692.66   504.2  694.21   514.3  696.69
   524.4  700.12   544.6  707.84   554.7   711.1   655.5   741.6   726.1  762.22
#Mann= 3 , 0 , 0
       0      .1       0   416.1    .045       0   431.1      .1       0
Bank Sta=416.1,431.1
XS Rating Curve= 0 ,0
Exp/Cntr=0.3,0.1

Chan Stop Cuts=-1
Use User Specified Reach Order=0